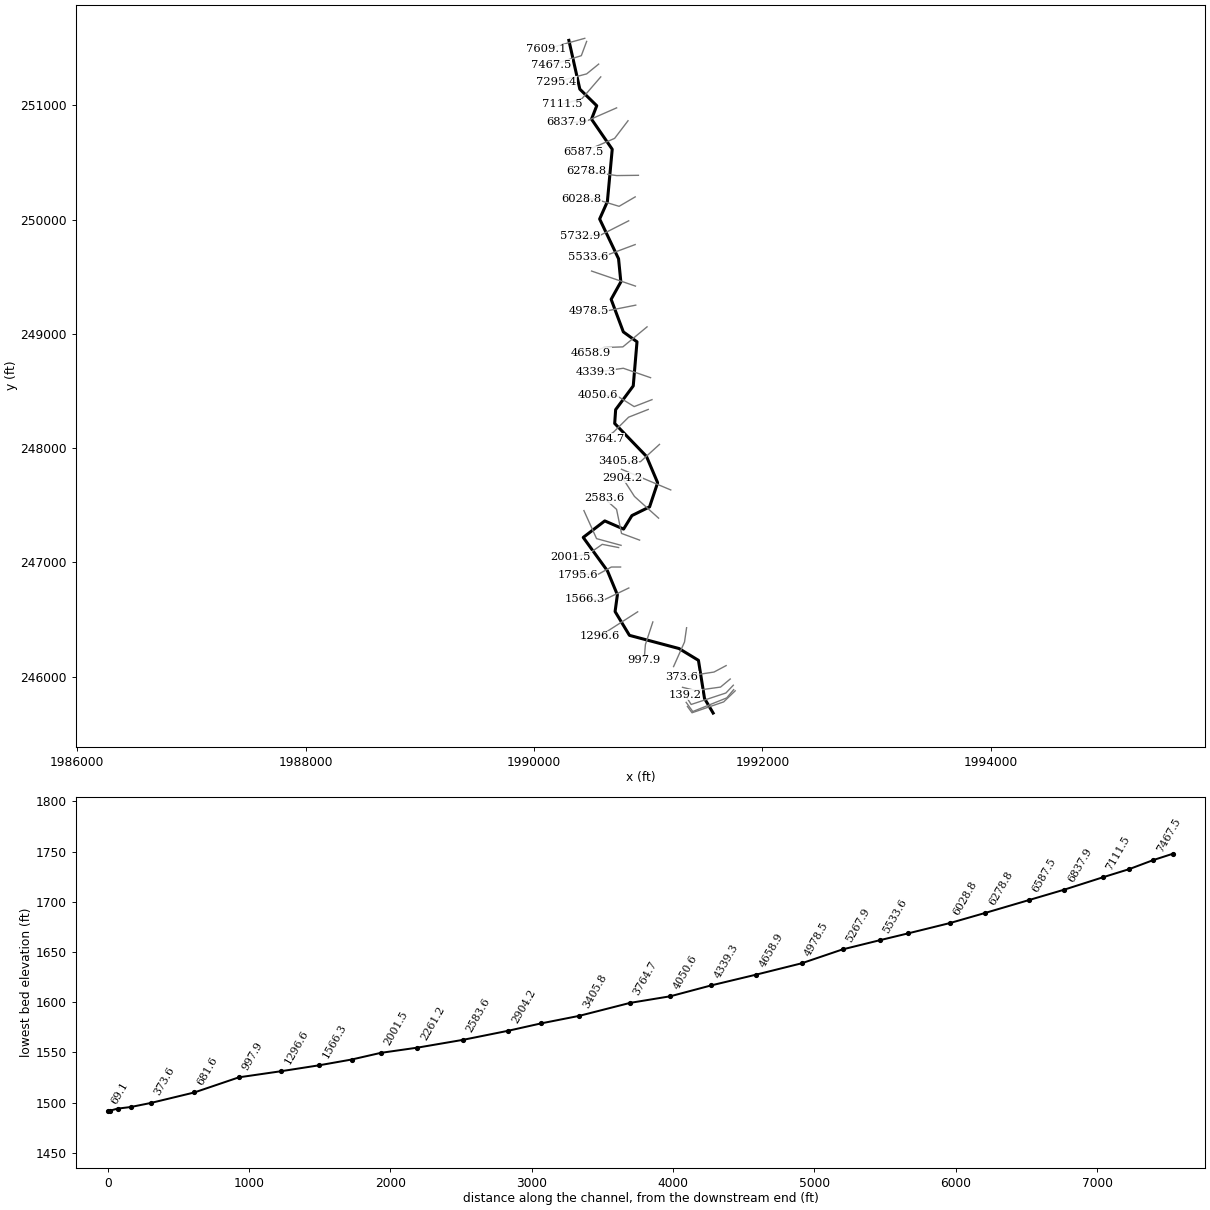
--- RFKMADAMCK.prj (project) ---

Proj Title=RFKMADAMCK
Current Plan=p01
Default Exp/Contr=0,0
English Units
Geom File=g01
Flow File=f01
Plan File=p01
BEGIN DESCRIPTION:
END DESCRIPTION:
DSS Export Rating Curves= 0
DSS Export Rating Curve Sorted= 0
DSS Export Volume Flow Curves= 0
DXF OffsetX= 0
DXF OffsetY= 0
DXF ScaleX= 0
DXF ScaleY= 0

--- RFKMADAMCK.p01 (plan) ---

Plan Title=Floodplain
Program Version=4.00
Geom File=g01
Flow File=f01
K Sum by GR=0
Std Step Tol=0.01
Critical Tol=0.01
Num of Std Step Trials=20
Max Error Tol=0.3
Flow Tol Ratio=0.001
Split Flow NTrial=30
Split Flow Tol=0.02
Split Flow Ratio=0.02
Log Output Level=0
Friction Slope Method=1
Unsteady Friction Slope Method=2
Unsteady Bridges Friction Slope Method=1
Global Log Level=0
CheckData=False
Run HTab=0
Run UNet=0
Run PostProcess=0
UNET Theta=0
UNET Theta Warmup=0
UNET ZTol=0
UNET ZSATol=0
UNET MxIter=0
UNET MaxInSteps=0
UNET DtIC=0
UNET DtMin=0
UNET MaxCRTS=0
UNET WFStab=0
UNET SFStab=0
UNET WFX=0
UNET SFX=0
UNET DSS MLevel=0
UNET DZMax Abort=0
UNET Convert EG Bridges=0
UNET Use Existing IB Tables=0
UNET Froude Limit=0
UNET Froude Power=0
Write IC File=0
Echo Input=False
Echo Output=False
Write Detailed=0

--- RFKMADAMCK.f01 (steady flow) ---

Flow Title=2010 USGS WV Regression Equation
Program Version=4.00
Number of Profiles=1
Profile Names=P100yr
River Rch & RM=RFKMADAMCK,Main      ,7609.1
495.8002
River Rch & RM=RFKMADAMCK,Main      ,7467.5
565.9801
River Rch & RM=RFKMADAMCK,Main      ,3405.8
604.6805
River Rch & RM=RFKMADAMCK,Main      ,2001.5
670.1015
River Rch & RM=RFKMADAMCK,Main      ,373.6
695.5722
River Rch & RM=RFKMADAMCK,Main      ,232
698.0513
Boundary for River Rch & Prof#=RFKMADAMCK,Main      ,1
Up Type=0
Dn Type=3
Dn Slope=0.03013

--- RFKMADAMCK.g01 (geometry) ---

Geom Title=LiDAR
Program Version=4.10

River Reach=RFKMADAMCK      ,Main
Reach XY= 30
     1990305.817      251568.691     1990401.705      251141.984
     1990549.914      250996.709     1990504.081      250879.001
     1990685.504      250615.807      1990642.97      250157.474
     1990575.262      250005.564     1990740.883      249657.632
     1990761.025      249455.216     1990675.956      249302.439
     1990782.727      249017.716     1990902.518      248930.911
     1990869.615      248544.808     1990715.448      248337.169
     1990707.115      248216.336     1990985.415      247928.205
     1991083.331      247697.736     1991012.724      247486.528
     1990857.809      247410.086     1990784.893       247292.03
     1990620.309      247363.558      1990431.42      247219.114
     1990643.684       246926.26     1990730.726      246717.037
     1990710.587      246570.502     1990836.281      246362.169
     1991270.309      246246.891     1991440.658      246143.451
      1991493.92      245809.391     1991569.451      245682.196

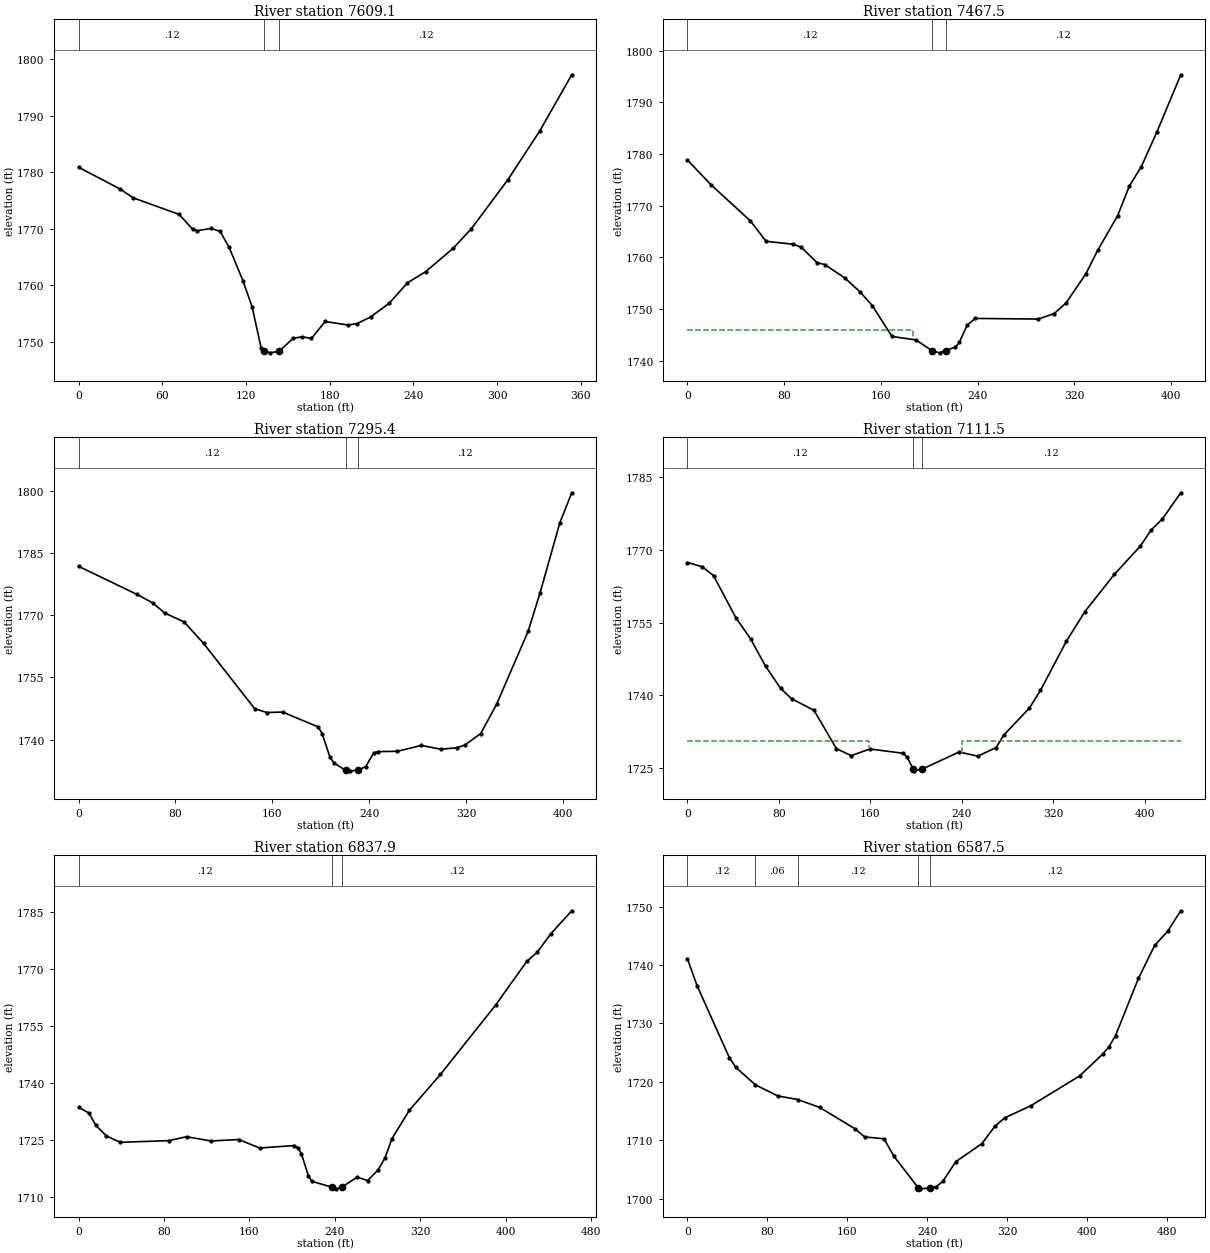
Type RM Length L Ch R = 1 ,7609.1  ,143.9,141.6,142.2
XS GIS Cut Line= 2
     1990445.127      251586.603     1990104.415      251492.382
#Sta/Elev= 30
       0 1780.86    29.5 1777.05    39.3 1775.43      72 1772.53    81.8 1769.88
    85.1 1769.63    94.9 1770.03   101.5 1769.51     108 1766.66   117.8  1760.8
   124.4 1756.17   130.9 1748.86  133.211748.334   137.5 1748.02     144 1748.33
   153.8  1750.6   160.4 1750.86   166.9 1750.57   176.8 1753.57   193.1 1752.94
   199.7  1753.2   209.5 1754.39   222.6 1756.78   235.7  1760.4   248.8 1762.39
   268.4 1766.49   281.5 1769.97   307.7 1778.65   330.6  1787.3   353.5 1797.22
#Mann= 3 ,-1 , 0
       0     .12       0  133.21    .045       0     144     .12       0
Bank Sta=133.21,144
XS Rating Curve= 0 ,0
Exp/Cntr=0.3,0.1

Type RM Length L Ch R = 1 ,7467.5  ,169.2,172.1,170.3
XS GIS Cut Line= 3
     1990461.403      251559.476     1990414.745      251434.693
     1990152.158      251353.313
#Sta/Elev= 30
       0 1778.82    19.5 1774.04      52 1767.08      65 1763.13    87.7 1762.55
    94.2 1761.95   107.2    1759   113.7 1758.62     130 1756.06     143  1753.3
   152.9  1750.7   169.2 1744.73   188.9 1744.07   202.2    1742   208.5 1741.57
  213.64 1742.02   221.6 1742.69   224.9 1743.59   231.4 1746.92     238 1748.22
   290.3  1748.1   303.4 1749.17   313.2 1751.21   329.6 1756.84   339.4 1761.39
   355.8 1768.04   365.6 1773.81   375.4 1777.53   388.5 1784.32   408.1 1795.31
#Mann= 3 ,-1 , 0
       0     .12       0   202.2    .045       0  213.64     .12       0
#XS Ineff= 2 , 0
          186.27 1746.08
Permanent Ineff=
       F       F
Bank Sta=202.2,213.64
XS Rating Curve= 0 ,0
Exp/Cntr=0.3,0.1

Type RM Length L Ch R = 1 ,7295.4  ,169.7,183.9,197.1
XS GIS Cut Line= 3
     1990566.654      251360.908     1990461.403      251275.368
     1990198.816      251205.924
#Sta/Elev= 30
       0 1781.79    48.4 1774.99    61.4 1772.94      71 1770.56    87.2 1768.36
   103.3 1763.18   145.4 1747.47   155.3 1746.54   168.4 1746.65   197.8 1743.09
   201.1 1741.47   207.6 1735.75   210.9 1734.36   220.7 1732.58     224 1732.48
   230.5  1732.6   237.1  1733.5   243.6 1736.76   246.9 1737.11   263.2 1737.19
   282.9 1738.61   299.2 1737.69   312.3 1738.04   318.9  1738.7     332 1741.46
   345.1  1748.5   371.2 1766.14   381.1 1775.46   397.4 1792.32   407.2 1799.51
#Mann= 3 ,-1 , 0
       0     .12       0   220.7    .045       0   230.5     .12       0
Bank Sta=220.7,230.5
XS Rating Curve= 0 ,0
Exp/Cntr=0.3,0.1

Type RM Length L Ch R = 1 ,7111.5  ,281.7,273.6,263.3
XS GIS Cut Line= 3
     1990585.101      251249.146     1990419.085      251057.089
     1990247.644      251010.431
#Sta/Elev= 30
       0 1767.45      13 1766.57    22.8 1764.72    42.3 1756.06    55.3 1751.65
    68.4 1745.99    81.4  1741.5    91.1 1739.32   110.7 1736.94   130.2 1729.05
   143.2 1727.58   159.5 1728.96   188.8 1728.07     192 1727.31  197.541724.807
   198.5 1724.45     205 1724.78   237.6 1728.34   253.9 1727.48     270 1729.26
   276.5 1731.78   299.1 1737.41   308.8 1741.07   331.4 1751.18   347.6  1757.3
   373.4    1765     396 1770.79   405.7 1774.19   415.4 1776.43   431.5 1781.84
#Mann= 3 ,-1 , 0
       0     .12       0  197.54    .045       0     205     .12       0
#XS Ineff= 2 , 0
          158.93 1730.64  240.45         1730.52
Permanent Ineff=
       F       F
Bank Sta=197.54,205
XS Rating Curve= 0 ,0
Exp/Cntr=0.3,0.1

Type RM Length L Ch R = 1 ,6837.9  ,249.9,250.4,249.8
XS GIS Cut Line= 3
     1990723.989      250978.059     1990446.212      250856.532
     1990287.791      250850.021
#Sta/Elev= 30
       0 1733.61     9.8 1732.02    16.3 1728.78    26.1 1726.04    39.1 1724.36
    84.8  1724.8   101.1 1725.83   123.9 1724.71     150 1725.09   169.5 1722.86
   202.1  1723.5   205.4 1722.93   208.6 1721.41   215.2 1715.55   218.4 1714.09
  236.871712.598   241.2 1712.12  246.761712.597   260.8 1715.21   270.6  1714.3
   280.4 1717.06   286.9 1720.21   293.4  1725.3   309.7 1732.76   338.8  1742.2
   390.6 1760.48   419.7 1771.95   429.4 1774.34   442.3 1779.24   461.8 1785.25
#Mann= 3 ,-1 , 0
       0     .12       0  236.87    .045       0  246.76     .12       0
Bank Sta=236.87,246.76
XS Rating Curve= 0 ,0
Exp/Cntr=0.3,0.1

Type RM Length L Ch R = 1 ,6587.5  ,321,308.7,295.2
XS GIS Cut Line= 3
     1990823.816      250865.212     1990706.628      250711.132
     1990431.021      250591.775
#Sta/Elev= 30
       0 1741.02     9.7 1736.42    41.9 1724.16    48.4  1722.5   67.991719.512
    90.3 1717.62  110.191716.999   132.3 1715.65   167.8 1711.98   177.4  1710.6
   196.8 1710.28   206.6 1707.32  230.981701.906   232.8 1701.72   242.6 1701.87
   249.1 1702.08   255.6    1703   268.7 1706.37   294.8 1709.46   307.8 1712.43
   317.6 1713.86   343.8 1715.94   392.7 1721.04   415.6 1724.75   422.1 1726.05
   428.6 1727.94   451.5  1737.7   467.8 1743.36   480.9  1745.8   493.9 1749.28
#Mann= 5 ,-1 , 0
       0     .12       0   67.99     .06       0  110.19     .12       0
  230.98    .045       0   242.6     .12       0
Bank Sta=230.98,242.6
XS Rating Curve= 0 ,0
Exp/Cntr=0.3,0.1

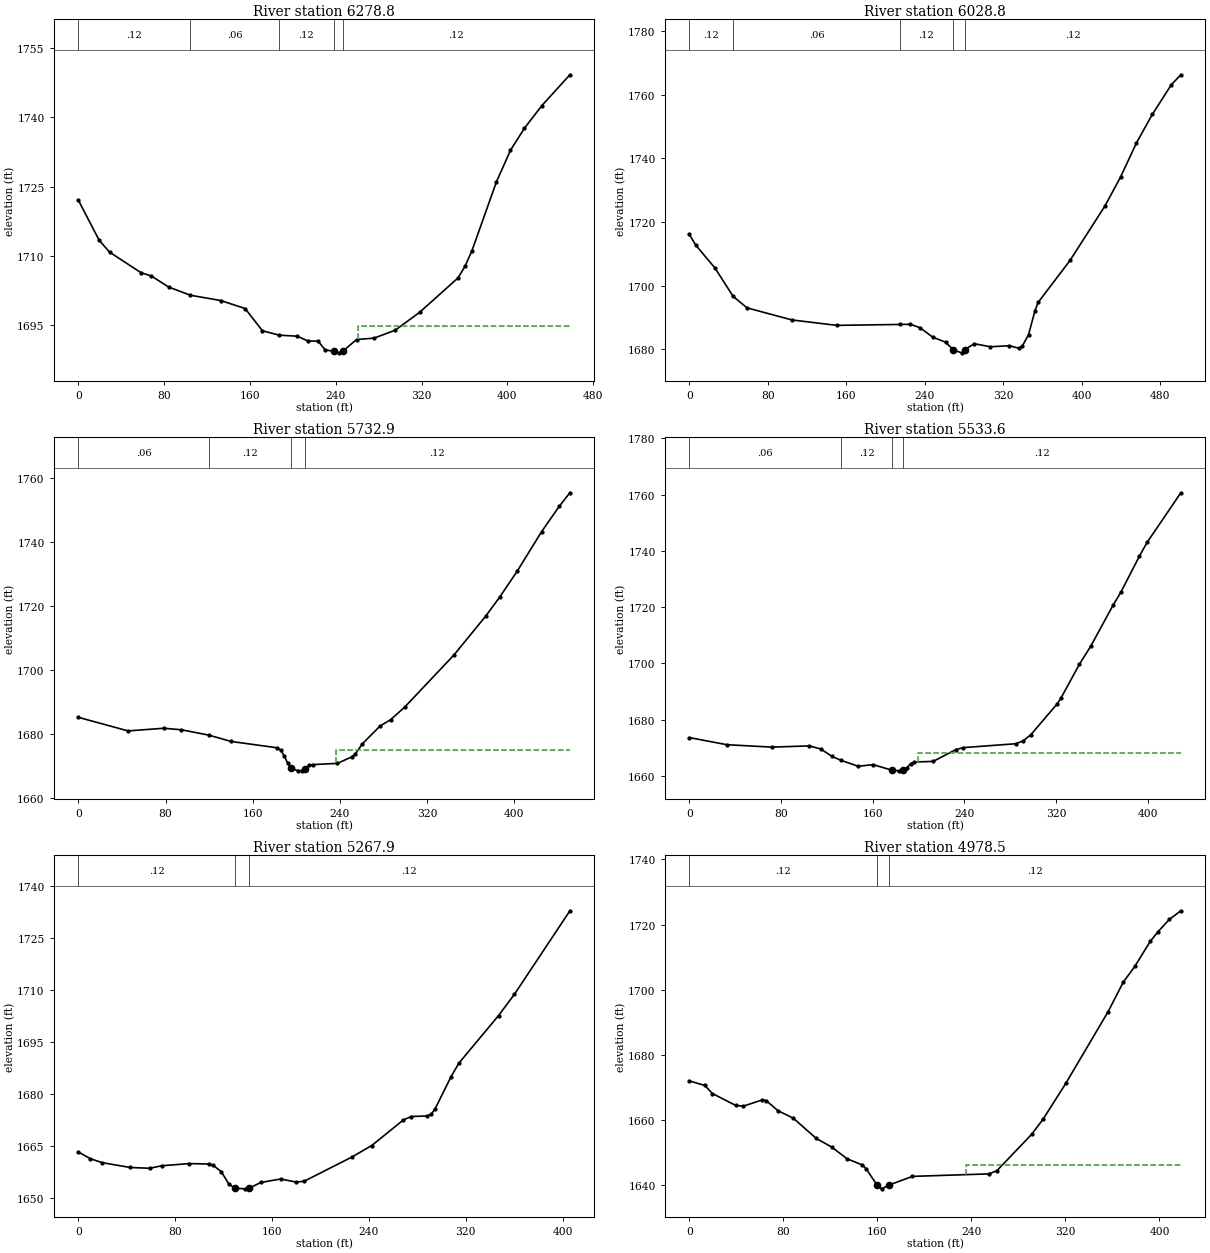
Type RM Length L Ch R = 1 ,6278.8  ,252.9,250,245.8
XS GIS Cut Line= 3
     1990914.962      250387.782     1990723.989      250385.612
     1990459.232      250422.504
#Sta/Elev= 30
       0    1722    19.4 1713.32    29.1 1710.76    58.3 1706.33      68  1705.6
    84.2  1703.2  104.421701.426   132.7 1700.28   155.4 1698.55   171.6 1693.72
  187.281692.769     204 1692.55   213.8 1691.53   223.6 1691.46   230.1 1689.57
  237.921689.286   243.1 1688.94   246.4 1689.27   259.4 1691.83   275.7 1692.13
   295.3 1693.83   318.1 1697.71     354 1705.19   360.5 1707.71     367  1711.1
   389.8 1726.02   402.9 1732.86   415.9 1737.63   432.2 1742.55   458.3 1749.22
#Mann= 5 ,-1 , 0
       0     .12       0  104.42     .06       0  187.28     .12       0
  237.92    .045       0   246.4     .12       0
#XS Ineff= 2 , 0
                          260.58         1694.66
Permanent Ineff=
       F       F
Bank Sta=237.92,246.4
XS Rating Curve= 0 ,0
Exp/Cntr=0.3,0.1

Type RM Length L Ch R = 1 ,6028.8  ,277.9,295.9,312.9
XS GIS Cut Line= 4
      1990886.75       250198.98     1990745.691      250116.514
     1990530.847      250181.618        1990418.      250183.789
#Sta/Elev= 30
       0 1716.06     6.5 1712.72    26.1 1705.51    44.71696.563    58.8 1692.98
   104.6 1689.18   150.3 1687.48  214.221687.769   225.2 1687.82     235 1686.74
     248 1683.77     261 1682.19  268.911679.792   277.3 1678.84   280.5 1679.81
   290.3 1681.71   306.6 1680.75   326.1 1681.08   335.8 1680.28   339.1 1680.91
   345.6 1684.53   352.1 1692.02   355.4 1694.71   387.9 1707.91   423.4    1725
   439.5  1734.2   455.6 1744.89   471.7  1753.8   491.1 1763.17   500.8 1766.29
#Mann= 5 ,-1 , 0
       0     .12       0    44.7     .06       0  214.22     .12       0
  268.91    .045       0   280.5     .12       0
Bank Sta=268.91,280.5
XS Rating Curve= 0 ,0
Exp/Cntr=0.3,0.1

Type RM Length L Ch R = 1 ,5732.9  ,201.8,199.3,196.2
XS GIS Cut Line= 3
      1990829.55      249989.621     1990582.698      249864.239
     1990408.451      249857.219
#Sta/Elev= 30
       0 1685.27    45.6 1681.03    78.2 1681.86    94.5 1681.39  119.781679.715
   140.1 1677.75   182.4 1675.76   185.7 1675.03   188.9 1673.29   192.2  1670.9
   195.4 1669.35     202 1668.56   205.2 1668.66  207.791669.288   211.7 1670.26
     215 1670.51   237.8 1670.89   250.8 1672.89   254.1 1673.76   260.6 1676.94
   276.9 1682.54   286.6 1684.52   299.5 1688.43   344.7  1704.7   373.8  1716.8
   386.7 1722.77   402.8 1730.87   425.4 1743.31   441.6 1751.22   451.3 1755.41
#Mann= 4 ,-1 , 0
       0     .06       0  119.78     .12       0   195.4    .045       0
  207.79     .12       0
#XS Ineff= 2 , 0
                          236.84         1675.03
Permanent Ineff=
       F       F
Bank Sta=195.4,207.79
XS Rating Curve= 0 ,0
Exp/Cntr=0.3,0.1

Type RM Length L Ch R = 1 ,5533.6  ,280.9,265.6,249.3
XS GIS Cut Line= 3
     1990886.316      249781.698     1990610.274      249678.833
      1990476.16      249672.323
#Sta/Elev= 30
       0  1673.6    32.7 1671.07      72 1670.21   104.7 1670.65   114.6 1669.56
   124.4 1666.93   132.31665.521   147.3  1663.4   160.4 1663.98   176.8    1662
   183.3 1661.78   186.6 1661.99   189.8 1662.85   193.1 1664.33   196.4 1664.92
   212.8 1665.14   232.4  1669.3   238.9 1670.03   284.8 1671.41   291.3 1672.42
   297.9 1674.58   320.8  1685.5   324.1 1687.51   340.4 1699.68   350.3  1706.1
   369.9 1720.77   376.5 1725.23   392.8 1738.13   399.4 1742.95   428.9 1760.62
#Mann= 4 ,-1 , 0
       0     .06       0   132.3     .12       0   176.8    .045       0
   186.6     .12       0
#XS Ineff= 2 , 0
                          199.17         1668.11
Permanent Ineff=
       F       F
Bank Sta=176.8,186.6
XS Rating Curve= 0 ,0
Exp/Cntr=0.3,0.1

Type RM Length L Ch R = 1 ,5267.9  ,275.9,289.5,300.7
XS GIS Cut Line= 2
      1990888.92      249418.417     1990504.805      249549.927
#Sta/Elev= 30
       0 1663.19     9.8 1661.26    19.6 1660.12    42.6 1658.73    58.9 1658.49
    68.8 1659.22    91.7 1659.85     108 1659.71   111.3 1659.35   117.9 1657.56
   124.4 1653.88  129.411652.751   137.5 1652.56   140.8  1652.7   150.6 1654.39
     167  1655.4   180.1  1654.5   186.6 1654.78   225.9 1661.73   242.3 1665.06
   268.5 1672.45     275 1673.43   288.1 1673.59   291.4 1674.07   294.7 1675.69
   307.8 1684.91   314.3 1688.83   347.1 1702.57   360.2 1708.71     406 1732.79
#Mann= 3 ,-1 , 0
       0     .12       0  129.41    .045       0   140.8     .12       0
Bank Sta=129.41,140.8
XS Rating Curve= 0 ,0
Exp/Cntr=0.3,0.1

Type RM Length L Ch R = 1 ,4978.5  ,307.6,319.6,330.4
XS GIS Cut Line= 3
     1990891.524       249251.75     1990615.482      249197.063
     1990478.764      249200.969
#Sta/Elev= 30
       0 1671.92    13.1  1670.5    19.6 1668.03    39.3 1664.39    45.8 1664.12
    62.2  1666.1    65.4 1665.85    75.3 1662.77    88.4 1660.45     108 1654.21
   121.1 1651.57   134.2 1647.96   147.2 1646.06   150.5 1644.86   159.5 1639.98
   163.6 1638.72   170.2 1639.92   189.8 1642.55   255.2 1643.32   261.8 1644.35
   291.2 1655.46     301 1660.15   320.5 1671.26   356.3 1693.19   369.3 1702.32
   379.1 1707.14   392.1 1714.78   398.6 1717.72   408.4 1721.55   418.2 1724.22
#Mann= 3 ,-1 , 0
       0     .12       0   159.5    .045       0   170.2     .12       0
#XS Ineff= 2 , 0
                          235.81         1645.95
Permanent Ineff=
       F       F
Bank Sta=159.5,170.2
XS Rating Curve= 0 ,0
Exp/Cntr=0.3,0.1

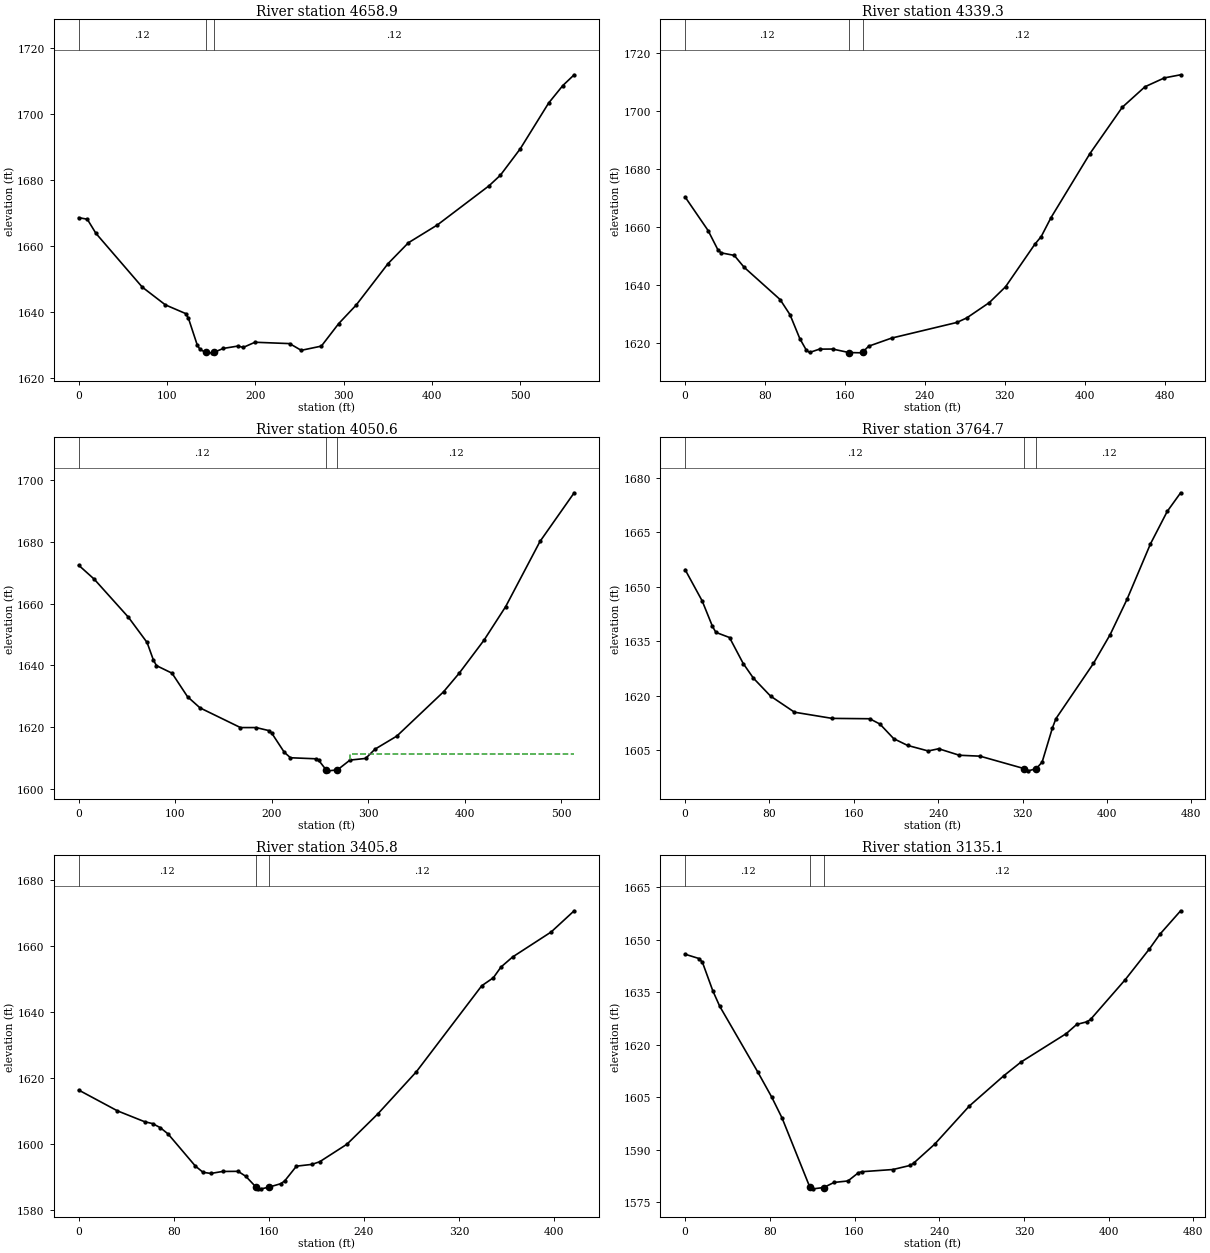
Type RM Length L Ch R = 1 ,4658.9  ,342.6,319.6,295.9
XS GIS Cut Line= 4
     1990990.482      249061.646     1990778.677       248886.48
     1990611.488      248880.536     1990502.201      248833.781
#Sta/Elev= 30
       0 1668.48     9.8    1668    19.6 1663.71      72 1647.43    98.2 1642.04
   121.1 1639.41   124.3 1637.99   134.2 1629.94   137.4 1628.52     144 1627.63
   150.5  1627.5   153.8  1627.7   163.6 1628.83     180 1629.54   186.5 1629.16
   199.6 1630.71   238.9  1630.3     252 1628.26   274.8 1629.54   294.5 1636.39
   314.2 1641.98   350.3 1654.55   373.3 1660.86   406.1 1666.26   464.6 1678.13
   477.5 1681.35     500 1689.36   532.1 1703.22   548.2 1708.53     561 1711.78
#Mann= 3 ,-1 , 0
       0     .12       0     144    .045       0   153.8     .12       0
Bank Sta=144,153.8
XS Rating Curve= 0 ,0
Exp/Cntr=0.3,0.1

Type RM Length L Ch R = 1 ,4339.3  ,292.5,288.7,282.6
XS GIS Cut Line= 3
     1991021.298      248616.948     1990782.583      248699.414
     1990541.698      248664.691
#Sta/Elev= 30
       0 1670.48      23 1658.91    32.8 1652.28    36.1 1651.21    49.2 1650.33
      59 1646.26    95.1  1635.1     105 1629.87   114.8 1621.63   121.4 1617.61
   124.6 1616.86   134.5 1618.01   147.6 1618.04     164 1616.83   177.1 1616.73
   177.8    1617   183.7 1619.02   206.6 1621.81     272 1627.21   281.8 1628.76
   304.5 1634.07   320.7 1639.52   349.9 1654.13   356.4 1656.84   366.1 1663.31
   405.1 1685.42   437.5 1701.41   460.2 1708.48   479.7 1711.54   495.9 1712.61
#Mann= 3 ,-1 , 0
       0     .12       0     164    .045       0   177.8     .12       0
Bank Sta=164,177.8
XS Rating Curve= 0 ,0
Exp/Cntr=0.3,0.1

Type RM Length L Ch R = 1 ,4050.6  ,254.7,285.9,315.6
XS GIS Cut Line= 4
     1991033.885      248424.674     1990877.635       248363.91
     1990732.236      248455.056     1990558.625      248465.907
#Sta/Elev= 30
       0 1672.42    16.1 1667.91    51.6 1655.57    70.9 1647.42    77.4 1641.77
    80.6 1639.94    96.7  1637.5   112.8 1629.88   125.7 1626.28   167.6 1619.91
   183.8 1619.91   196.8 1618.95     200 1618.11     213 1611.91   219.4 1610.15
   245.4 1609.82   248.6 1609.33  256.311606.243   258.3 1605.92     268 1606.22
     281 1609.39   297.2 1609.93   306.9 1612.92   329.5 1617.15   377.9 1631.47
     394 1637.44   419.8 1648.16   442.3 1659.05   477.8 1680.09   513.2 1695.83
#Mann= 3 ,-1 , 0
       0     .12       0  256.31    .045       0     268     .12       0
#XS Ineff= 2 , 0
                          281.11         1611.49
Permanent Ineff=
       F       F
Bank Sta=256.31,268
XS Rating Curve= 0 ,0
Exp/Cntr=0.3,0.1

Type RM Length L Ch R = 1 ,3764.7  ,359.3,358.9,357.3
XS GIS Cut Line= 4
     1991000.899       248338.99     1990829.024      248271.281
     1990698.816      248142.375     1990615.482      248083.781
#Sta/Elev= 30
       0 1654.69    16.2 1646.07    25.9  1639.1    29.2 1637.41    42.1    1636
    55.1 1628.84    64.8  1624.8      81 1619.88   103.7 1615.44   139.4 1613.74
     175 1613.64   184.7 1612.18   197.8 1608.15   210.9  1606.3   230.5 1604.77
   240.4 1605.38     260 1603.59   279.6 1603.34   321.6  1599.9   325.4  1599.3
     333 1599.91   338.5 1601.72   348.3 1611.17   351.6 1613.68   387.1 1628.85
     403 1636.81   418.9 1646.47   441.2 1661.78   457.1 1670.72   469.8 1675.84
#Mann= 3 ,-1 , 0
       0     .12       0   321.6    .045       0     333     .12       0
Bank Sta=321.6,333
XS Rating Curve= 0 ,0
Exp/Cntr=0.3,0.1

Type RM Length L Ch R = 1 ,3405.8  ,295.9,270.7,243.4
XS GIS Cut Line= 3
     1991099.423      248033.181     1990932.323      247881.271
     1990741.351      247889.952
#Sta/Elev= 30
       0 1616.38    32.7 1610.06    55.6 1606.76    62.2  1606.2    68.7 1604.97
    75.3 1603.05    98.2 1593.33   104.7 1591.42   111.3 1591.08   121.1 1591.68
   134.2 1591.72   140.7  1590.2  149.131586.989   150.6 1586.51   153.8 1586.41
   160.4 1586.95   170.2 1587.98   173.5 1588.86   183.3 1593.29   196.4 1593.83
   202.9 1594.64   225.8 1599.95   251.8 1609.15   284.2 1621.92   339.2    1648
     349 1650.44   355.4 1653.68   365.2 1656.74   397.6 1664.31     417 1670.75
#Mann= 3 ,-1 , 0
       0     .12       0  149.13    .045       0   160.4     .12       0
Bank Sta=149.13,160.4
XS Rating Curve= 0 ,0
Exp/Cntr=0.3,0.1

Type RM Length L Ch R = 1 ,3135.1  ,238.3,230.9,224
XS GIS Cut Line= 2
     1991198.108      247634.614     1990766.524      247815.552
#Sta/Elev= 30
       0 1645.87    13.1 1644.65    16.4 1643.55    26.2 1635.41    32.7 1631.01
    68.7 1612.21    81.8 1605.08    91.6 1599.09   117.8 1579.37   121.1 1578.88
   130.9 1579.26   140.7 1580.71   153.8 1581.13   163.6 1583.46   166.9 1583.77
   196.4  1584.4   212.7 1585.58     216 1586.26   235.6  1591.6   268.4 1602.52
   301.1  1611.2   317.4 1615.12     360 1623.21   369.8 1625.82   379.6 1626.59
   382.9 1627.25   415.6 1638.58   438.5 1647.38   448.3 1651.54     468 1658.28
#Mann= 3 ,-1 , 0
       0     .12       0   117.8    .045       0   130.9     .12       0
Bank Sta=117.8,130.9
XS Rating Curve= 0 ,0
Exp/Cntr=0.3,0.1

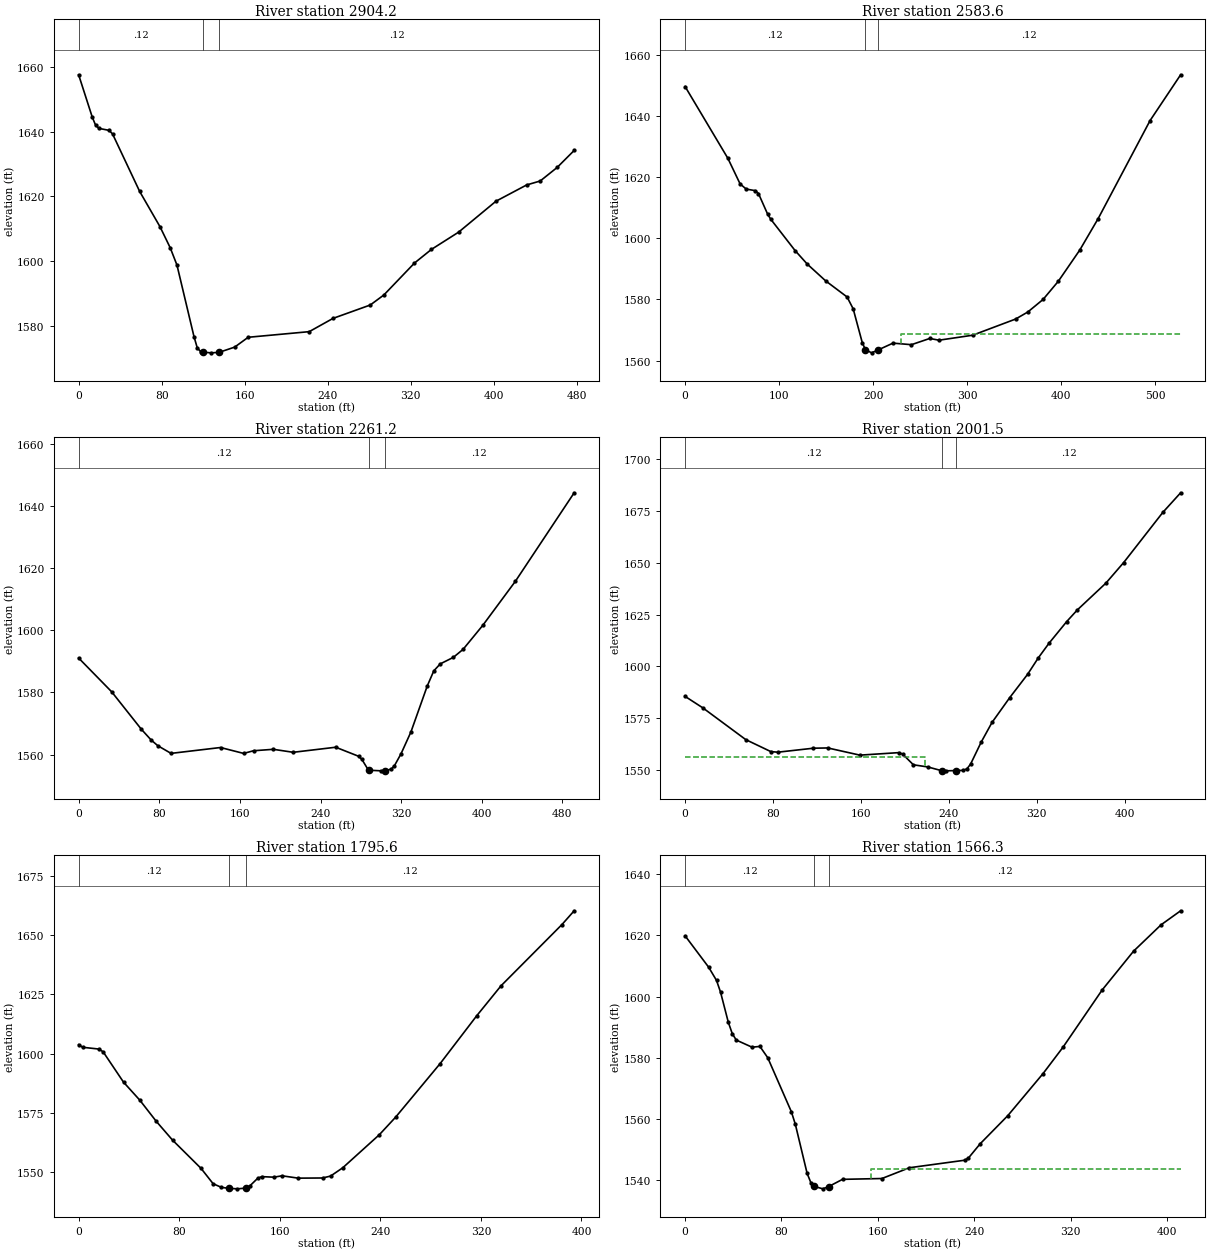
Type RM Length L Ch R = 1 ,2904.2  ,334.6,320.6,304.9
XS GIS Cut Line= 3
     1991091.611      247387.782     1990880.217       247577.73
     1990775.639      247740.031
#Sta/Elev= 30
       0 1657.57    13.1  1644.5    16.3 1642.02    19.6 1640.99    29.4 1640.38
    32.7 1639.26    58.8 1621.49    78.4 1610.57    88.2 1604.09    94.7 1598.74
   111.1 1576.63   114.3 1573.09   117.6 1571.95   120.1 1571.79   127.4 1571.59
   135.1 1571.72   150.3 1573.36   163.3  1576.4   222.1 1578.14     245 1582.24
   280.9 1586.38     294 1589.48   323.5 1599.36   339.8 1603.57     366 1608.91
     402 1618.48   431.5  1623.5   444.6 1624.73   460.9 1628.91   477.3 1634.17
#Mann= 3 ,-1 , 0
       0     .12       0   120.1    .045       0   135.1     .12       0
Bank Sta=120.1,135.1
XS Rating Curve= 0 ,0
Exp/Cntr=0.3,0.1

Type RM Length L Ch R = 1 ,2583.6  ,316.4,322.4,327.3
XS GIS Cut Line= 4
     1990925.378      247195.507     1990766.958      247254.101
     1990723.555      247464.605     1990617.219      247560.091
#Sta/Elev= 30
       0 1649.75    45.5 1626.22    58.5 1617.84      65 1616.16    74.7 1615.64
      78  1614.7    87.7 1607.98      91 1606.31   116.9 1596.03   129.9 1591.58
   149.4  1586.1   172.2 1580.82   178.7 1576.92   188.4  1565.8   191.7 1563.59
   198.2 1562.52   205.2 1563.47     221  1565.7   240.6 1565.19   260.1 1567.23
   269.9 1566.66   305.7 1568.29   351.3 1573.58   364.3 1575.89   380.6 1580.02
   396.8 1585.98   419.6  1596.2   439.1 1606.48   494.3  1638.6   526.8  1653.6
#Mann= 3 ,-1 , 0
       0     .12       0   191.7    .045       0   205.2     .12       0
#XS Ineff= 2 , 0
                          229.72         1568.78
Permanent Ineff=
       F       F
Bank Sta=191.7,205.2
XS Rating Curve= 0 ,0
Exp/Cntr=0.3,0.1

Type RM Length L Ch R = 1 ,2261.2  ,217.3,259.7,300.5
XS GIS Cut Line= 3
     1990763.052      247149.934     1990548.208      247208.528
     1990437.531      247453.754
#Sta/Elev= 30
       0 1591.07    32.8 1580.19    62.2 1568.15      72 1564.66    78.6 1562.83
    91.7 1560.37   140.8 1562.26   163.7 1560.36   173.6 1561.22   193.2 1561.68
   212.9 1560.72   255.1 1562.35   277.8 1559.44     281 1558.46   287.5    1555
   288.6 1554.94   300.5 1554.75   303.6 1554.76   310.2  1555.3   313.4 1556.42
   319.9 1560.24   329.7 1567.25   345.9 1582.05   352.4 1586.93   358.8 1589.18
   371.8 1591.28   381.5 1593.87     401 1601.58   433.4 1615.79   491.7 1644.27
#Mann= 3 ,-1 , 0
       0     .12       0   288.6    .045       0   303.6     .12       0
Bank Sta=288.6,303.6
XS Rating Curve= 0 ,0
Exp/Cntr=0.3,0.1

Type RM Length L Ch R = 1 ,2001.5  ,208.1,205.9,203.4
XS GIS Cut Line= 4
     1990741.351      247130.403     1990598.121      247158.615
     1990470.083      247069.639     1990322.514      247050.108
#Sta/Elev= 30
       0 1585.48    16.2 1579.92    55.2 1564.61    77.9 1558.85    84.3 1558.54
   116.8 1560.47   129.8 1560.59     159 1557.12   194.7 1558.34     198 1557.55
   207.7 1552.45   220.7 1551.43   233.7 1549.57   236.9 1549.54   246.7 1549.67
   253.2 1549.77   256.4 1550.52   259.7 1552.78   269.4 1563.44   279.2  1572.9
   295.4 1584.94   311.6 1596.15   321.3 1604.07     331  1611.1   347.2 1621.63
   356.9 1627.27   382.8 1640.16     399 1650.11   434.6 1674.31   450.8 1683.78
#Mann= 3 ,-1 , 0
       0     .12       0   233.7    .045       0   246.7     .12       0
#XS Ineff= 2 , 0
          218.27 1556.22
Permanent Ineff=
       F       F
Bank Sta=233.7,246.7
XS Rating Curve= 0 ,0
Exp/Cntr=0.3,0.1

Type RM Length L Ch R = 1 ,1795.6  ,230.4,229.2,227.8
XS GIS Cut Line= 4
     1990758.712      246960.083     1990677.473      246959.952
     1990564.701      246897.583     1990380.673      246894.292
#Sta/Elev= 30
       0 1603.75     3.2 1602.65    16.2 1601.89    19.5 1600.73    35.7 1587.94
    48.7 1580.31    61.7 1571.44    74.7 1563.48    97.4 1551.54     107 1545.07
   113.5 1543.56   119.3 1543.14   126.3 1542.92   132.8 1543.22     136 1544.06
   142.4 1547.35   145.7 1548.07   155.3 1547.84   161.8 1548.42   174.7 1547.43
     194  1547.5   200.4  1548.3   210.1  1551.8   239.2 1565.75   252.1 1573.12
   287.6 1595.78   316.7 1615.96     336 1628.58   384.5 1654.44   394.2 1660.24
#Mann= 3 ,-1 , 0
       0     .12       0   119.3    .045       0   132.8     .12       0
Bank Sta=119.3,132.8
XS Rating Curve= 0 ,0
Exp/Cntr=0.3,0.1

Type RM Length L Ch R = 1 ,1566.3  ,266.5,269.7,272
XS GIS Cut Line= 3
      1990830.76      246776.671     1990609.767      246670.778
     1990443.607      246678.833
#Sta/Elev= 30
       0 1619.83    19.6 1609.56    26.1 1605.25    29.4 1601.47    35.9 1591.56
    39.2 1587.84    42.5 1585.78    55.6 1583.45    62.1 1583.71    68.6 1580.02
    88.2 1562.39    91.5 1558.31   101.3 1542.25   104.6 1539.03   107.4 1537.97
   114.4 1537.19  119.171537.933   130.7 1540.29   163.4 1540.56   186.2 1544.08
     232 1546.53   235.2 1547.24     245 1551.92   267.9 1561.09   297.2 1574.85
   313.6 1583.37   346.2 1602.12   372.3 1614.81   395.1 1623.41   411.4 1628.01
#Mann= 3 ,-1 , 0
       0     .12       0   107.4    .045       0  119.17     .12       0
#XS Ineff= 2 , 0
                          154.28         1543.72
Permanent Ineff=
       F       F
Bank Sta=107.4,119.17
XS Rating Curve= 0 ,0
Exp/Cntr=0.3,0.1

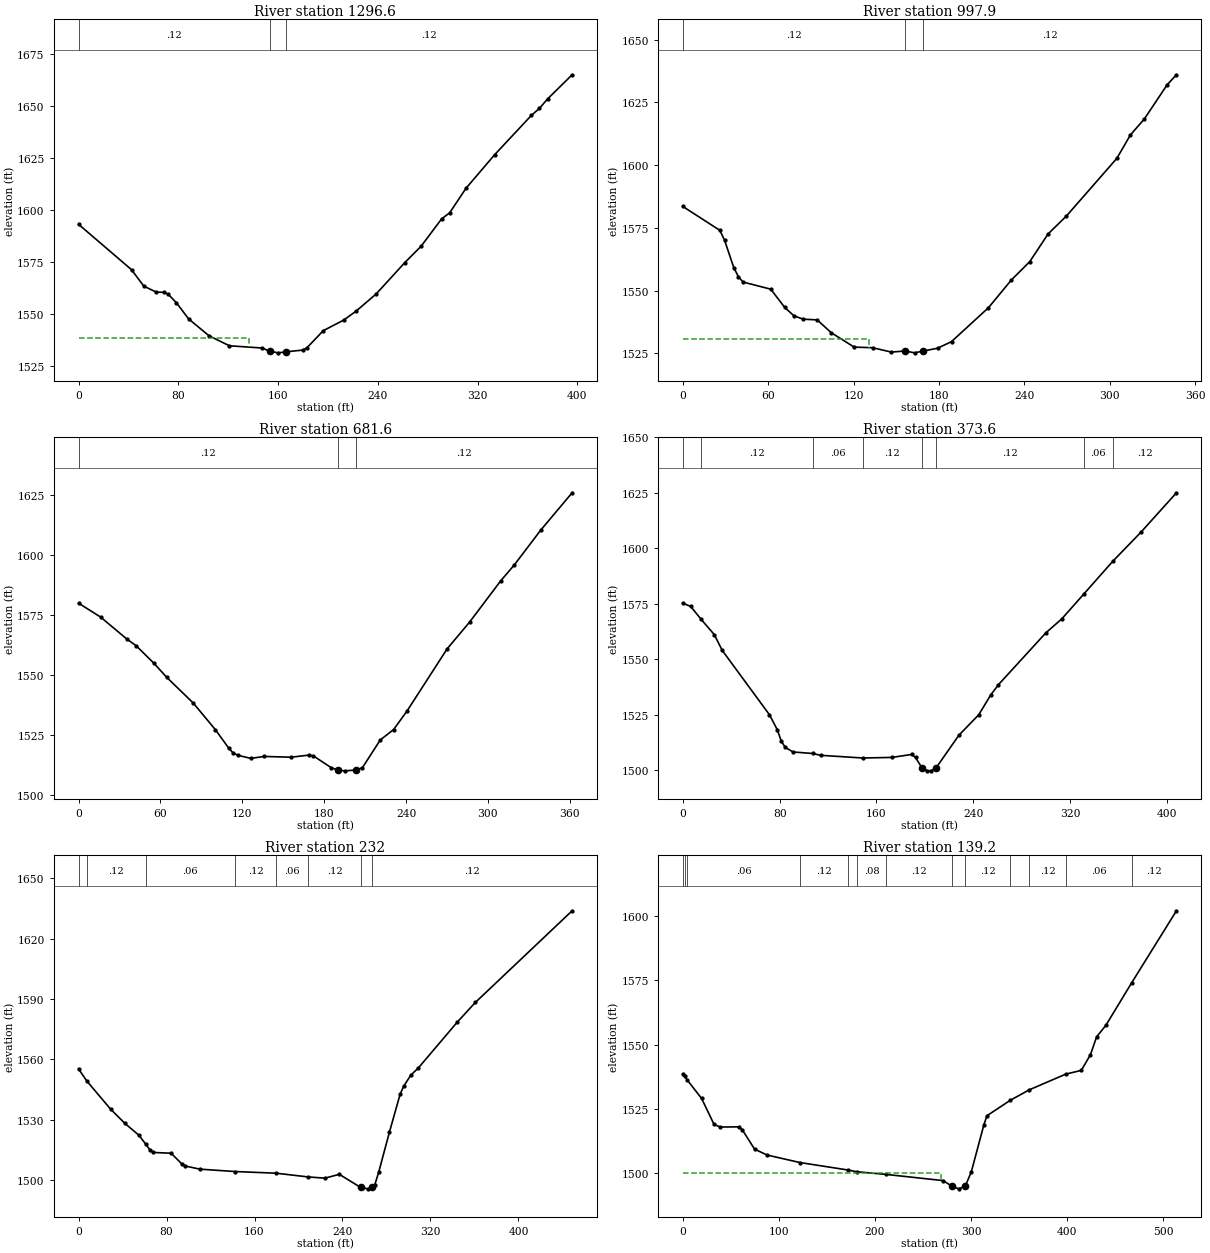
Type RM Length L Ch R = 1 ,1296.6  ,282.8,298.7,313.9
XS GIS Cut Line= 2
     1990908.451      246568.156     1990575.118      246354.615
#Sta/Elev= 30
       0  1593.1    42.5 1571.26    52.4 1563.32    62.2 1560.53    68.7 1560.34
      72 1559.41    78.5 1555.37    88.3  1547.6   104.7 1539.46     121 1534.68
   147.2  1533.6   153.8 1531.96   160.3 1531.28   166.8  1531.8   179.9 1532.61
   183.2 1533.71   196.3 1541.94   212.7 1547.04   222.5 1551.28   238.8 1559.64
   261.7 1574.68   274.8 1582.57   291.2 1595.68   297.7 1598.63   310.8 1610.43
   333.7 1626.51   363.2 1645.45   369.7 1648.85   376.2 1653.37   395.9 1664.99
#Mann= 3 ,-1 , 0
       0     .12       0   153.8    .045       0   166.8     .12       0
#XS Ineff= 2 , 0
          137.05 1538.38
Permanent Ineff=
       F       F
Bank Sta=153.8,166.8
XS Rating Curve= 0 ,0
Exp/Cntr=0.3,0.1

Type RM Length L Ch R = 1 ,997.9   ,317.6,316.3,313.1
XS GIS Cut Line= 3
     1991041.264      246479.615      1990976.16      246281.698
     1990964.441      246143.677
#Sta/Elev= 30
       0 1583.53      26 1574.02    29.3 1570.09    35.8 1559.15    39.1 1555.49
    42.3 1553.41    61.8 1550.56    71.6 1543.28    78.1 1539.94    84.6  1538.6
    94.4 1538.33   104.2 1533.25   120.4 1527.48   133.5 1527.22   146.5 1525.49
   156.3 1525.93   162.8 1525.19  168.541525.865     179 1527.03   188.8 1529.66
   214.8  1543.2   230.9 1554.25   243.8 1561.54   256.7  1572.6   269.6 1579.75
     305 1602.71   314.6  1612.1   324.3 1618.39   340.4 1632.08   346.9 1636.03
#Mann= 3 ,-1 , 0
       0     .12       0   156.3    .045       0  168.54     .12       0
#XS Ineff= 2 , 0
          131.11 1530.74
Permanent Ineff=
       F       F
Bank Sta=156.3,168.54
XS Rating Curve= 0 ,0
Exp/Cntr=0.3,0.1

Type RM Length L Ch R = 1 ,681.6   ,330.2,308,284.9
XS GIS Cut Line= 3
     1991336.837      246428.833     1991318.676      246303.945
      1991222.84      246088.795
#Sta/Elev= 30
       0 1579.85    16.2 1574.04    35.6 1564.82    42.1  1562.2      55 1554.98
    64.7 1548.95    84.1 1538.26   100.3  1527.2     110 1519.57   113.3 1517.49
   116.5 1516.59   126.2 1515.26     136 1516.07   155.6 1515.75   168.7 1516.61
     172 1516.33   185.1 1511.42   189.9 1510.43   194.9 1510.08  202.991510.381
     208 1511.38   221.1 1522.92   230.9 1527.27   240.7 1534.96   270.1 1560.84
   286.5 1571.92   309.4 1589.16   319.2 1595.66   338.8 1610.31   361.7 1625.77
#Mann= 3 ,-1 , 0
       0     .12       0   189.9    .045       0  202.99     .12       0
Bank Sta=189.9,202.99
XS Rating Curve= 0 ,0
Exp/Cntr=0.3,0.1

Type RM Length L Ch R = 1 ,373.6   ,141.6,141.6,141
XS GIS Cut Line= 3
     1991683.191      246097.417     1991576.854      246040.993
     1991292.566      245997.591
#Sta/Elev= 30
       0 1575.21     6.5 1573.74   15.231567.861      26 1561.04    32.5 1553.96
    71.6  1524.9    78.1  1518.1    81.3 1513.11    84.6 1510.19    91.1 1508.13
  107.271507.443   113.9 1506.62  148.771505.409   172.7 1505.67     189    1507
   192.3 1505.65  197.621500.985   202.1 1499.62   205.4 1499.69   209.31500.957
   228.2 1515.69   244.6 1524.92   254.4 1533.77   260.9  1538.5   300.1 1561.87
   313.2 1568.14  331.481579.382  355.261594.051   378.6  1607.2     408    1625
#Mann= 8 ,-1 , 0
       0    .016       0   15.23     .12       0  107.27     .06       0
  148.77     .12       0  197.62    .045       0   209.3     .12       0
  331.48     .06       0  355.26     .12       0
Bank Sta=197.62,209.3
XS Rating Curve= 0 ,0
Exp/Cntr=0.3,0.1

Type RM Length L Ch R = 1 ,232     ,88.8,92.8,96.9
XS GIS Cut Line= 4
     1991718.998      245980.049     1991634.363      245909.519
     1991415.179      245879.137     1991301.246      245907.349
#Sta/Elev= 30
       0 1555.22    7.461549.239    29.2 1535.18    42.1 1528.16    55.1 1522.15
   61.011517.853    64.8 1515.05      68 1513.69    84.2  1513.3      94 1507.96
    97.2 1506.94   110.2  1505.4  142.091504.215  179.681503.383  208.761501.523
   224.1 1500.92   237.1 1502.83   256.6 1496.28   263.1 1495.61  266.741496.279
   269.4 1497.68   272.9 1503.83   282.6 1523.63   292.4 1542.63   295.7 1546.65
   302.2 1552.17   308.7 1555.51   344.5 1578.53   360.8 1588.23   448.8 1633.78
#Mann= 8 ,-1 , 0
       0    .016       0    7.46     .12       0   61.01     .06       0
  142.09     .12       0  179.68     .06       0  208.76     .12       0
   256.6    .045       0  266.74     .12       0
Bank Sta=256.6,266.74
XS Rating Curve= 0 ,0
Exp/Cntr=0.3,0.1

Type RM Length L Ch R = 1 ,139.2   ,53.5,54.9,56.3
XS GIS Cut Line= 4
     1991746.125      245925.795      1991681.17      245857.667
     1991376.762      245757.291     1991324.033       245841.16
#Sta/Elev= 30
       0 1538.64    1.731537.699    4.21 1536.41    19.5 1529.09    32.5 1518.98
      39 1517.99    58.4 1518.07    61.7 1517.02    74.6 1509.43    87.6 1507.13
  121.891504.214  172.061501.302  180.751500.653  211.861499.592   270.8 1497.21
     280 1495.06   287.1 1494.01  293.95 1495.09   300.2 1500.61   313.3 1518.89
   316.5 1522.38  340.941528.416  360.721532.467  398.471538.523   414.7 1539.97
   424.2 1546.08   430.6    1553   440.2 1557.44  467.171574.016   513.7 1601.91
#Mann= 13 ,-1 , 0
       0    .016       0    1.73     .12       0    4.21     .06       0
  121.89     .12       0  172.06    .016       0  180.75     .08       0
  211.86     .12       0     280    .045       0  293.95     .12       0
  340.94     .06       0  360.72     .12       0  398.47     .06       0
  467.17     .12       0
#XS Ineff= 2 , 0
          269.16 1500.06
Permanent Ineff=
       F       F
Bank Sta=280,293.95
XS Rating Curve= 0 ,0
Exp/Cntr=0.3,0.1

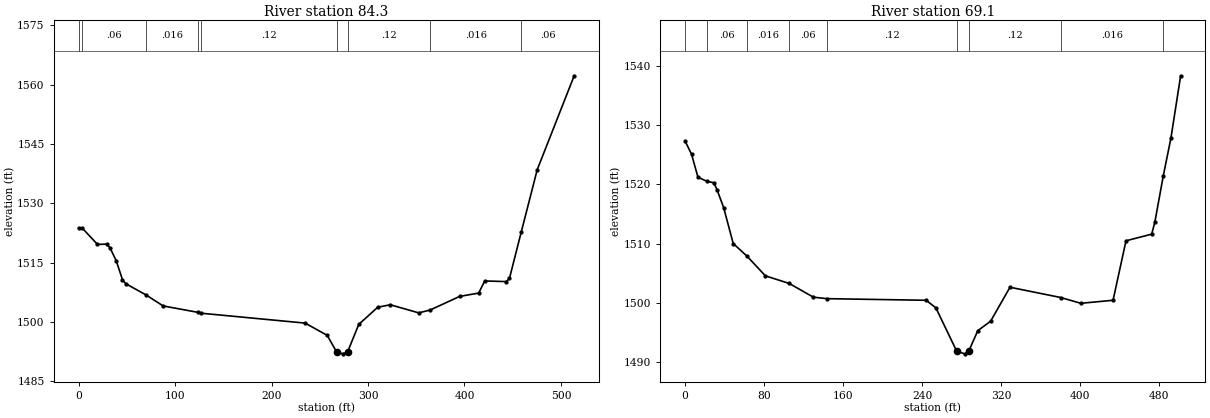
Type RM Length L Ch R = 1 ,84.3    ,16.3,15.2,14
XS GIS Cut Line= 4
     1991749.059      245886.881      1991688.54      245814.785
     1991391.084      245695.371     1991333.159       245775.74
#Sta/Elev= 30
       0 1523.78    3.831523.698    19.5  1519.6    29.2 1519.66    32.5 1518.74
      39 1515.45    45.4  1510.7    48.7 1509.68      701506.801    87.6 1504.04
  123.821502.415  127.061502.197   234.8  1499.7   257.7  1496.6   267.5 1492.38
     274 1491.93  278.821492.412   290.4 1499.37     310  1503.7   323.1 1504.34
   352.5 1502.29  364.261502.994     395 1506.45   414.7 1507.29     421 1510.36
   443.4 1510.19   446.6 1510.99  458.831522.714   475.4 1538.48   513.7 1562.22
#Mann= 9 ,-1 , 0
       0     .12       0    3.83     .06       0      70    .016       0
  123.82     .06       0  127.06     .12       0   267.5    .045       0
  278.82     .12       0  364.26    .016       0  458.83     .06       0
Bank Sta=267.5,278.82
XS Rating Curve= 0 ,0
Exp/Cntr=0.3,0.1

Type RM Length L Ch R = 1 ,69.1    ,65.4,69.1,72.8
XS GIS Cut Line= 4
     1991762.618       245876.75     1991661.923      245779.962
     1991384.363      245684.693     1991344.215      245740.031
#Sta/Elev= 30
       0  1527.3     6.5 1525.09      13 1521.21   22.221520.497    29.2 1520.26
    32.5    1519      39 1516.08    48.7 1510.01   62.75 1507.86    81.2 1504.56
  105.381503.267   129.9 1500.95  143.841500.701     244 1500.43   253.8 1499.15
   274.91491.825   283.1 1491.39  287.041491.831   296.2  1495.3   309.2  1496.9
   328.8 1502.63  380.171500.895   400.5 1499.92   433.1 1500.43   446.2 1510.47
   472.2 1511.59   475.4 1513.62  483.951521.442   491.7 1527.83   501.5 1538.32
#Mann= 9 ,-1 , 0
       0     .12       0   22.22     .06       0   62.75    .016       0
  105.38     .06       0  143.84     .12       0   274.9    .045       0
  287.04     .12       0  380.17    .016       0  483.95     .06       0
Bank Sta=274.9,287.04
XS Rating Curve= 0 ,0
Exp/Cntr=0.3,0.1

Chan Stop Cuts=-1
Use User Specified Reach Order=0
Composite Channel Slope=5